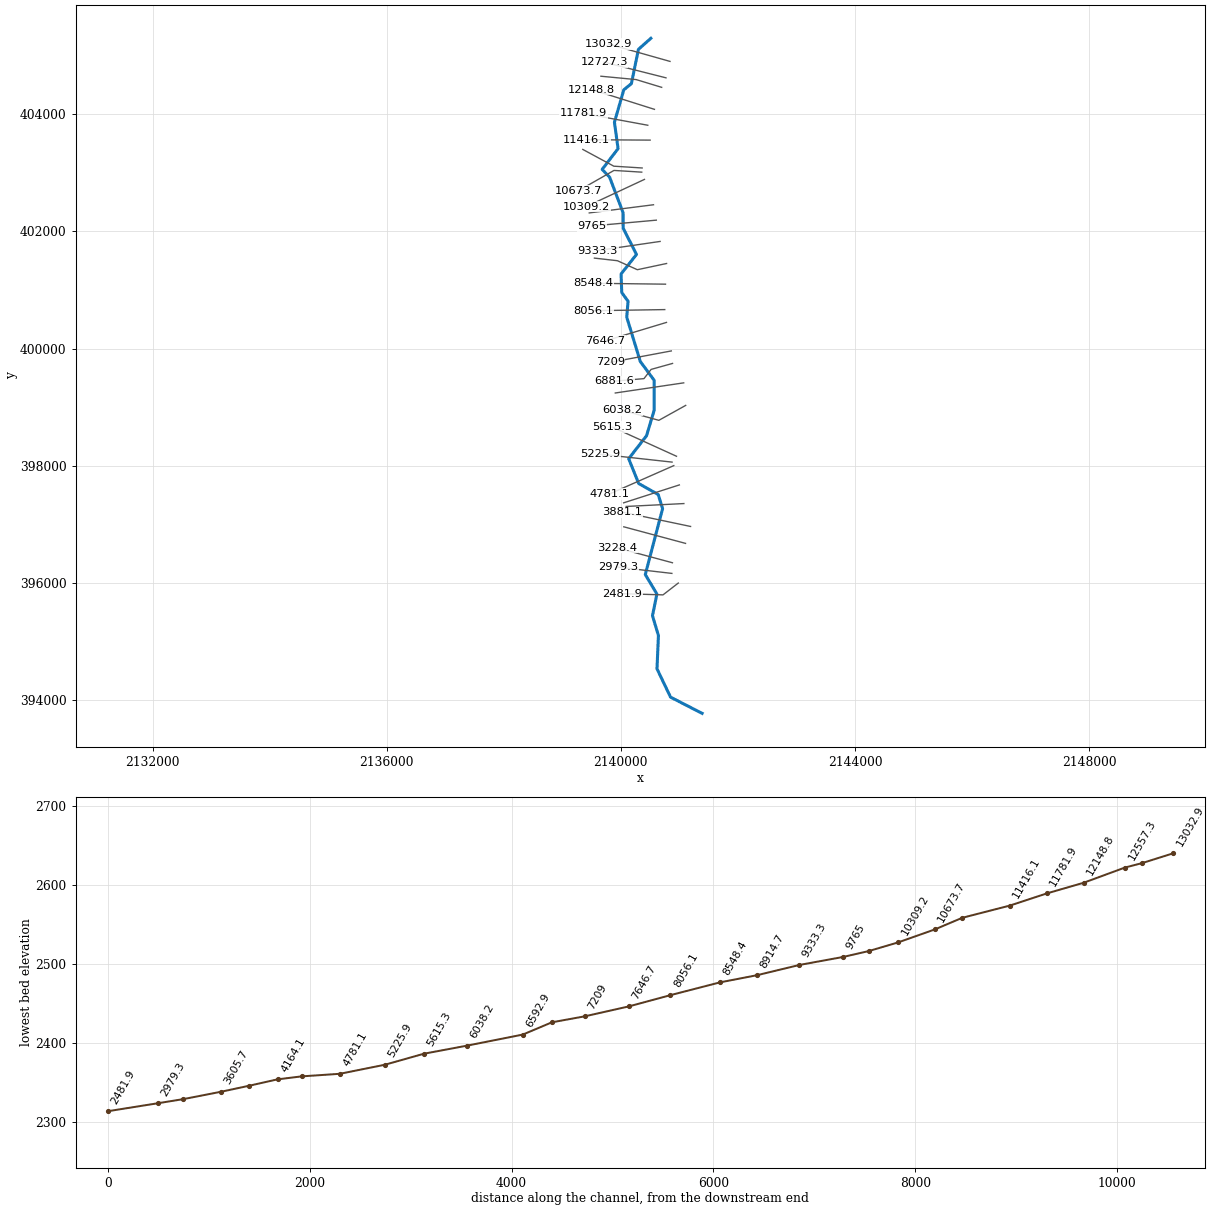
--- PantCampCk.prj (project) ---

Proj Title=PantCampCk
Current Plan=p01
Geom File=g01
Flow File=f01
Plan File=p01
DSS Export Rating Curves=0
DSS Export Rating Curve Sorted=0
DSS Export Volume Flow Curves=0
DXF OffsetX=0
DXF OffsetY=0
DXF ScaleX=0
DXF ScaleY=0

--- PantCampCk.p01 (plan) ---

Plan Title=Floodplain
Program Version=4.00
Geom File=g01
Flow File=f01
K Sum by GR=0
Std Step Tol=0.01
Critical Tol=0.01
Num of Std Step Trials=20
Max Error Tol=0.3
Flow Tol Ratio=0.001
Split Flow NTrial=30
Split Flow Tol=0.02
Split Flow Ratio=0.02
Log Output Level=0
Friction Slope Method=1
Unsteady Friction Slope Method=2
Unsteady Bridges Friction Slope Method=1
Global Log Level=0
CheckData=False
Run HTab=0
Run UNet=0
Run PostProcess=0
UNET Theta=0
UNET Theta Warmup=0
UNET ZTol=0
UNET ZSATol=0
UNET MxIter=0
UNET MaxInSteps=0
UNET DtIC=0
UNET DtMin=0
UNET MaxCRTS=0
UNET WFStab=0
UNET SFStab=0
UNET WFX=0
UNET SFX=0
UNET DSS MLevel=0
UNET DZMax Abort=0
UNET Convert EG Bridges=0
UNET Use Existing IB Tables=0
UNET Froude Limit=0
UNET Froude Power=0
Write IC File=0
Echo Input=False
Echo Output=False
Write Detailed=0

--- PantCampCk.f01 (steady flow) ---

Flow Title=NFF Regression Equation
Program Version=4.00
Number of Profiles=1
Profile Names=P100yr
River Rch & RM=PantCampCk,Main      ,13032.9
543.8262
River Rch & RM=PantCampCk,Main      ,10020.7
600.3024
River Rch & RM=PantCampCk,Main      ,9765
855.0302
River Rch & RM=PantCampCk,Main      ,8056.1
937.9553
River Rch & RM=PantCampCk,Main      ,6592.9
976.9660
River Rch & RM=PantCampCk,Main      ,544.7
1084.900
River Rch & RM=PantCampCk,Main      ,308
2827.128
Boundary for River Rch & Prof#=PantCampCk,Main      ,1
Up Type=0
Dn Type=3
Dn Slope=0.016419

--- PantCampCk.g01 (geometry) ---

Geom Title=USGS 10m DEM
Program Version=4.10

River Reach=PantCampCk      ,Main
Reach XY= 30
     2140512.616      405297.293     2140299.842      405109.221
     2140179.991      404524.729     2140049.394      404416.626
     2139890.074      403864.555     2139952.208      403414.329
     2139679.991      403059.104     2139807.292      402928.236
     2140037.804      402320.042     2140039.523      402056.178
     2140266.605       401607.32     2140003.429      401274.729
     2140014.918      400956.875     2140122.691      400809.131
     2140100.304      400537.229      2140331.49       399780.96
     2140569.054      399459.104     2140569.054      398948.166
     2140438.613       398513.53     2140133.561      398120.881
     2140304.074      397697.264     2140637.804      397509.104
      2140712.86      397268.145     2140417.189      396142.726
     2140615.614      395810.787     2140539.896      395440.079
     2140641.792      395101.726     2140617.166      394533.426
     2140848.742      394049.729     2141388.267      393772.909

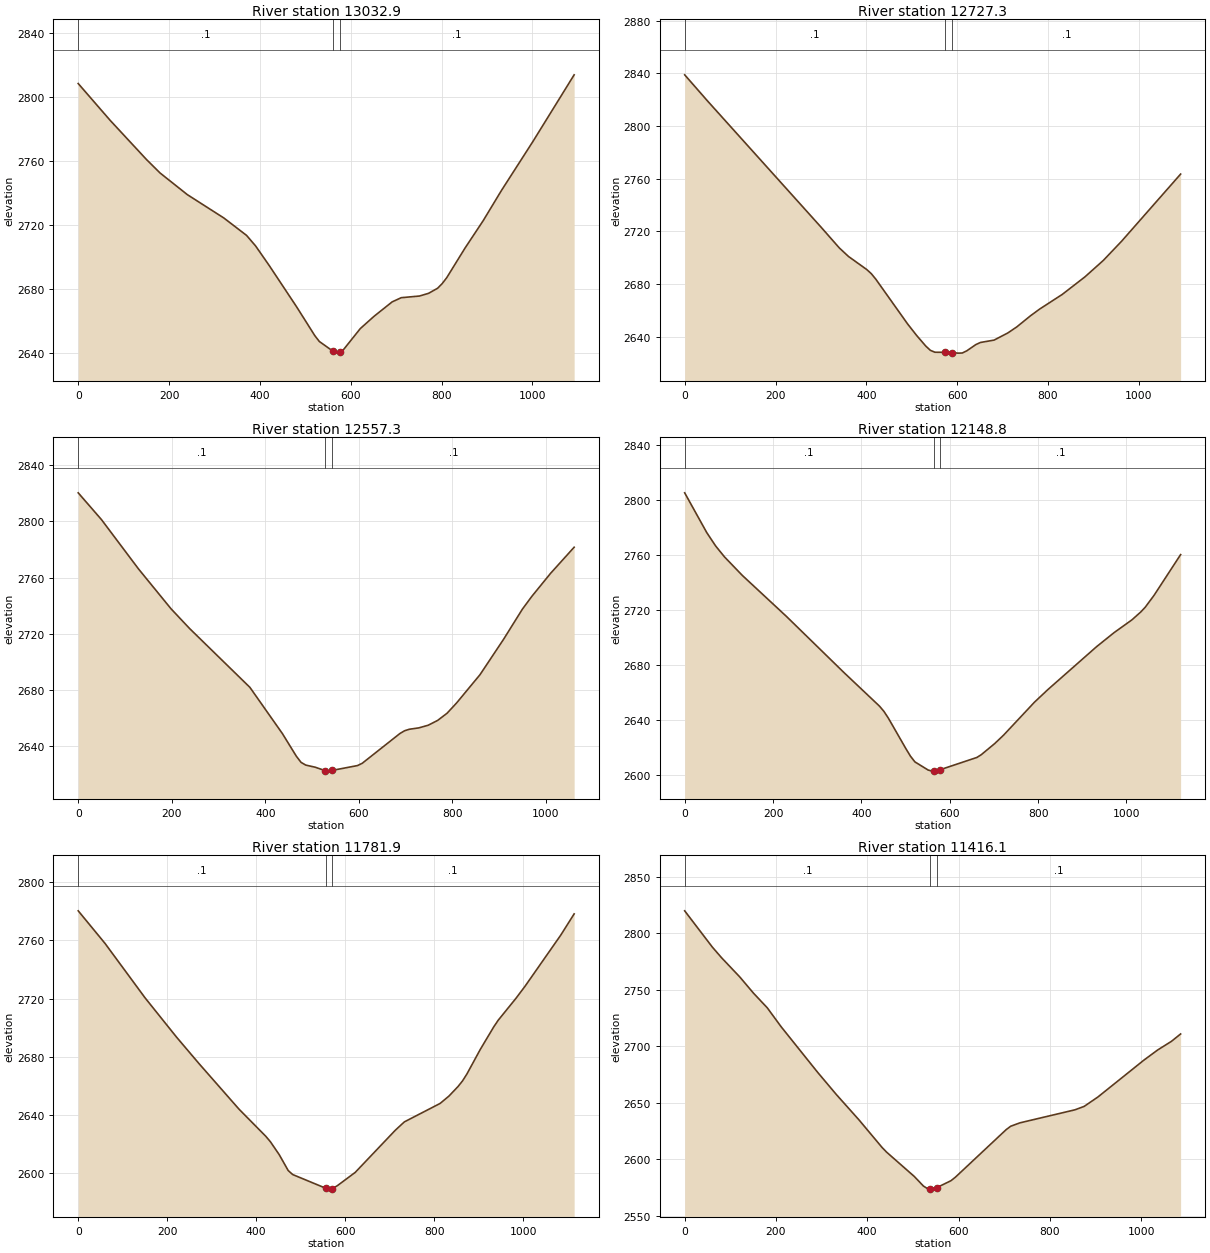
Type RM Length L Ch R = 1 ,13032.9 ,304.9,305.5,306.1
XS GIS Cut Line= 2
     2140839.539      404903.487     2139788.602      405200.125
#Sta/Elev= 30
       0 2808.38    70.1 2785.42   150.3 2760.84   180.3 2752.39   240.4 2738.84
   320.6 2724.27   370.7 2713.36   390.7 2706.73   420.8 2694.42   480.9 2668.68
     521 2650.64     531 2646.98   561.2 2640.88     571 2639.71   576.2 2640.28
   581.1 2640.82   621.1 2655.05   651.2  2662.7   691.3 2671.78   711.3 2674.39
   751.4 2675.43   771.4 2677.11   791.4 2680.31   801.5 2683.22   811.5 2686.93
   851.6 2705.38   891.6 2722.52   931.7 2741.36  1001.8 2772.38    1092 2813.82
#Mann= 3 , 0 , 0
       0      .1       0   561.2    .045       0   576.2      .1       0
Bank Sta=561.2,576.2
XS Rating Curve= 0 ,0
Exp/Cntr=0.3,0.1

Type RM Length L Ch R = 1 ,12727.3 ,166.6,170,173.7
XS GIS Cut Line= 2
     2140770.883      404623.042     2139712.176      404890.628
#Sta/Elev= 30
       0  2838.9    50.1 2819.13   300.6 2723.04   340.6 2707.34   360.7 2700.89
   400.7 2691.02   410.8 2687.86   420.8 2683.66   490.9 2649.61   510.9 2640.82
     531 2632.77     541 2629.57     551 2628.13   573.5 2628.06   588.5 2627.89
   601.1 2627.45   611.1 2627.52   621.1 2629.19   641.2 2633.95   651.2 2635.54
   681.2 2637.34   711.3 2642.73   731.3 2647.38   761.4 2655.81   781.4 2660.87
   831.5 2672.08   881.6 2685.47   921.7 2697.85   961.8 2712.37    1092 2763.48
#Mann= 3 , 0 , 0
       0      .1       0   573.5    .045       0   588.5      .1       0
Bank Sta=573.5,588.5
XS Rating Curve= 0 ,0
Exp/Cntr=0.3,0.1

Type RM Length L Ch R = 1 ,12557.3 ,413.1,408.5,403.5
XS GIS Cut Line= 3
     2140697.035      404460.767     2140260.416      404593.287
     2139659.192       404650.48
#Sta/Elev= 30
       0 2820.46    49.6 2801.39     129  2766.1   198.4  2737.7   238.1 2723.61
     367 2681.62   436.4 2648.67   466.4 2632.42   476.4 2628.06   486.5 2626.12
   506.6 2624.62   528.5 2622.09   536.8 2621.82   543.5 2622.38   597.2  2625.8
   607.3 2627.45   687.8 2648.68   697.9 2650.66   707.9 2651.71   728.1 2652.68
   748.2 2654.58   768.3    2658   788.4  2663.1   808.6 2670.36   858.9 2690.64
   909.2 2715.85   949.5  2737.4   969.6  2746.5  1009.9 2763.03  1060.2 2781.63
#Mann= 3 , 0 , 0
       0      .1       0   528.5    .045       0   543.5      .1       0
Bank Sta=528.5,543.5
XS Rating Curve= 0 ,0
Exp/Cntr=0.3,0.1

Type RM Length L Ch R = 1 ,12148.8 ,364.1,366.9,369.6
XS GIS Cut Line= 2
     2140573.552       404085.19     2139502.958      404423.103
#Sta/Elev= 30
       0 2805.27    50.1 2776.25    70.2 2766.53    90.2  2758.6   130.3  2745.2
   230.6 2715.21   360.8 2674.34     441 2649.96   451.1 2646.13   461.1 2641.22
   501.2 2618.77   511.2 2613.49   521.2 2609.37   551.3  2603.4   561.3 2602.64
   563.6 2602.75   578.6  2603.7   661.6 2612.61   671.6 2614.65   701.7 2622.66
   721.7 2628.76   791.9 2652.85   821.9 2661.92   932.2 2693.18   972.3 2703.53
  1012.4 2712.76  1032.4 2718.49  1042.5 2721.95  1062.5  2730.6  1122.7 2760.29
#Mann= 3 , 0 , 0
       0      .1       0   563.6    .045       0   578.6      .1       0
Bank Sta=563.6,578.6
XS Rating Curve= 0 ,0
Exp/Cntr=0.3,0.1

Type RM Length L Ch R = 1 ,11781.9 ,361.7,365.8,369.6
XS GIS Cut Line= 2
     2140459.894       403813.51     2139363.796      404015.474
#Sta/Elev= 30
       0 2780.27    60.2 2757.91   150.6 2720.35   220.9 2693.54   271.1 2675.45
   361.5 2643.98   421.7 2625.34   431.8 2621.69   451.8 2612.75   471.9 2601.87
     482  2599.1   556.1 2589.72   562.3 2589.08   571.1 2589.43   582.4 2591.44
   622.5 2600.56   712.9 2629.61     733 2635.27   813.3 2647.94   833.4 2653.06
   853.5 2659.52   863.5 2663.33   873.6 2668.18   903.7 2685.08   933.8 2700.49
   943.8 2705.06     984 2720.23  1004.1 2728.41  1084.4 2763.53  1114.6 2778.17
#Mann= 3 , 0 , 0
       0      .1       0   556.1    .045       0   571.1      .1       0
Bank Sta=556.1,571.1
XS Rating Curve= 0 ,0
Exp/Cntr=0.3,0.1

Type RM Length L Ch R = 1 ,11416.1 ,481.7,470.3,458.4
XS GIS Cut Line= 2
     2140500.347      403559.629     2139413.681      403566.604
#Sta/Elev= 30
       0 2819.79    60.4 2787.84    80.5 2778.46   120.7 2761.35   150.9 2746.95
   181.1 2733.99   211.3 2717.34   291.8 2676.79     332 2657.54   382.4 2634.76
   432.7  2610.5   442.7 2606.36   503.1 2584.96   523.2 2576.45   533.3 2573.89
   537.7 2573.83   543.3 2573.75   552.7 2575.14   583.6 2581.22   593.6 2584.45
   704.3  2626.3   714.4 2629.35   734.5 2632.34   855.3 2643.88   875.4 2646.91
   905.6 2655.24  1006.2 2687.78  1036.4 2696.76  1066.6 2704.41  1086.7 2710.93
#Mann= 3 , 0 , 0
       0      .1       0   537.7    .045       0   552.7      .1       0
Bank Sta=537.7,552.7
XS Rating Curve= 0 ,0
Exp/Cntr=0.3,0.1

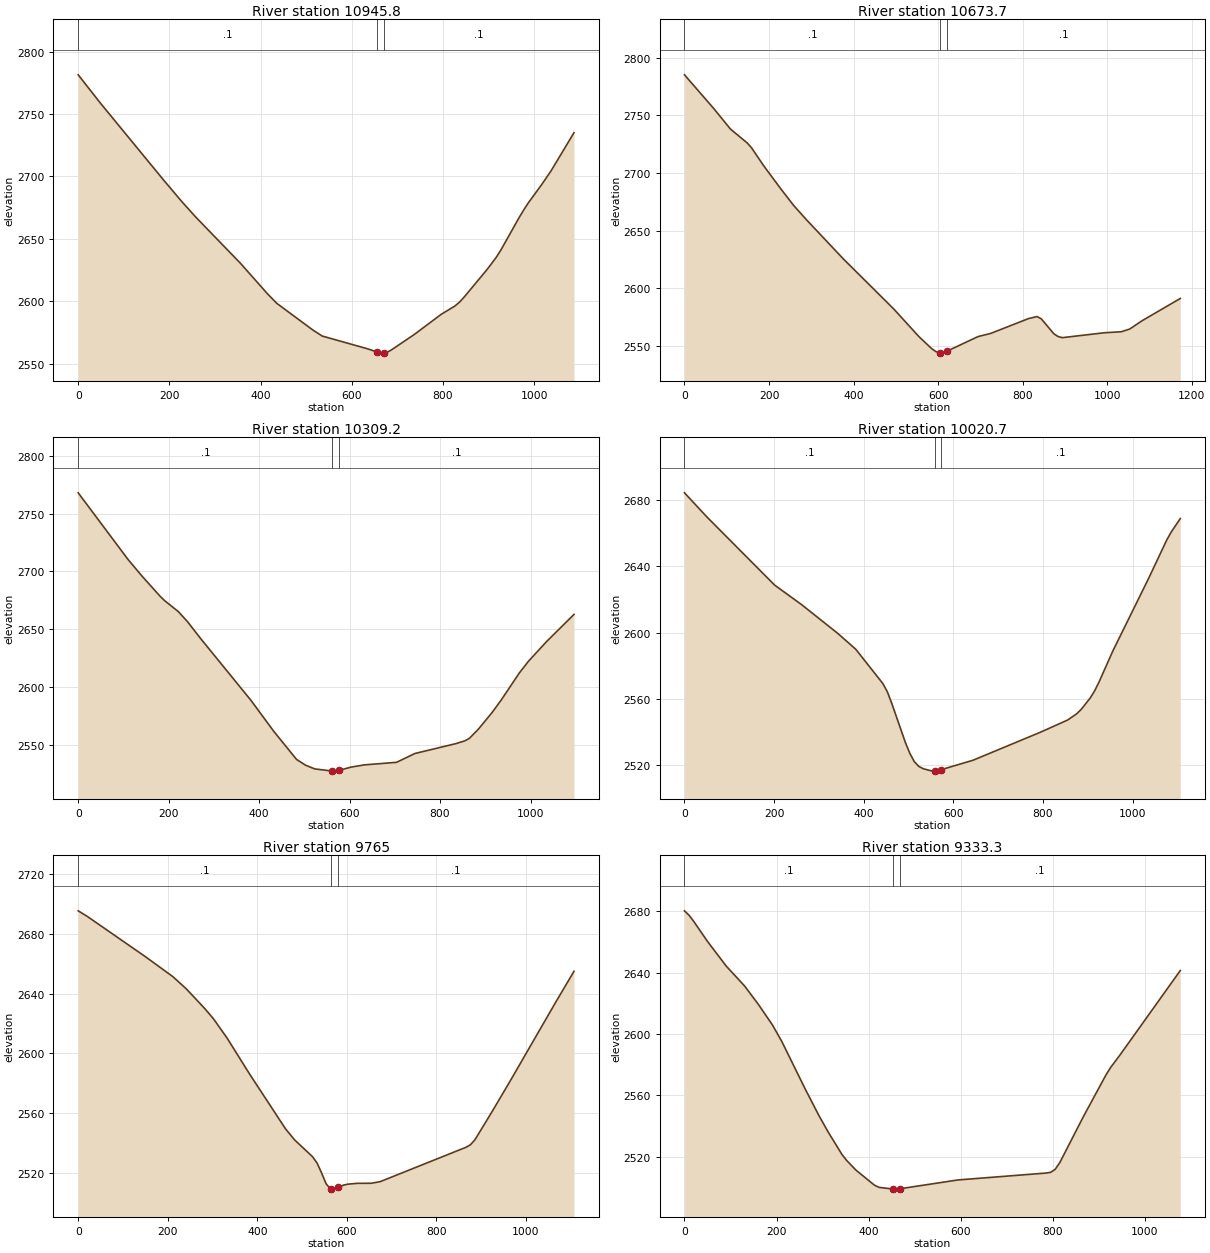
Type RM Length L Ch R = 1 ,10945.8 ,249.2,272.1,294.5
XS GIS Cut Line= 3
     2140363.642      403083.951     2139879.594       403114.64
     2139349.513      403400.604
#Sta/Elev= 30
       0 2781.49    49.5 2758.44   188.1 2696.77   227.7 2679.66   257.4  2667.6
   356.3 2630.21   415.7 2605.69   435.5  2598.3   515.1 2576.77   535.2 2572.05
   635.6 2561.72   655.9 2559.18   665.7 2558.36   670.9 2558.57   675.8 2558.76
   685.8 2560.67     736 2573.04   796.2 2589.49   826.3 2596.18   836.4 2599.31
   846.4 2603.29   896.6 2625.37   916.7 2635.12   926.7 2640.85   966.9 2666.98
   976.9 2673.04   986.9  2678.7    1017 2693.77  1037.1 2704.54  1087.3 2735.11
#Mann= 3 , 0 , 0
       0      .1       0   655.9    .045       0   670.9      .1       0
Bank Sta=655.9,670.9
XS Rating Curve= 0 ,0
Exp/Cntr=0.3,0.1

Type RM Length L Ch R = 1 ,10673.7 ,366,364.5,363.5
XS GIS Cut Line= 3
     2140356.667      403012.808     2139882.384      403042.102
     2139276.262      402696.432
#Sta/Elev= 30
       0 2785.06    69.3 2755.78   108.9 2737.96   148.5 2725.94   158.4 2721.88
   188.1  2705.8   227.7 2686.25   257.4 2672.14   287.1 2659.92   376.2 2625.24
   495.1 2581.94   554.9 2557.88   584.8 2547.55   594.8 2544.96   604.8 2543.64
   604.9 2543.65   619.9 2545.14   694.5    2558   724.4 2560.73   814.1 2573.62
     834 2575.36     844 2573.46   873.9 2560.42   883.9 2558.05   893.8 2557.06
   993.5 2561.31  1033.4 2562.18  1053.3 2564.54  1083.2 2571.88    1173 2591.05
#Mann= 3 , 0 , 0
       0      .1       0   604.9    .045       0   619.9      .1       0
Bank Sta=604.9,619.9
XS Rating Curve= 0 ,0
Exp/Cntr=0.3,0.1

Type RM Length L Ch R = 1 ,10309.2 ,296.7,288.5,280
XS GIS Cut Line= 2
     2140403.054      402889.155     2139409.849      402425.425
#Sta/Elev= 30
       0 2767.98   110.6 2710.11   140.8 2696.07     181 2678.56   191.1 2674.69
   221.2 2665.29   241.4 2656.64   271.5 2641.51   382.1 2588.38   432.4 2561.65
   482.7 2537.36   502.8 2532.33   522.9 2529.15   561.9 2527.26   563.2 2527.22
   576.9 2527.88   603.4 2530.71   633.5 2532.65   703.9 2534.84   744.2 2542.45
   834.7 2550.99   854.8 2553.44   864.8 2555.55     885 2563.64   915.1 2577.95
   935.2 2588.73   975.4 2612.21   995.6 2622.33  1035.8 2639.44  1096.1 2662.79
#Mann= 3 , 0 , 0
       0      .1       0   561.9    .045       0   576.9      .1       0
Bank Sta=561.9,576.9
XS Rating Curve= 0 ,0
Exp/Cntr=0.3,0.1

Type RM Length L Ch R = 1 ,10020.7 ,255.3,255.7,255.9
XS GIS Cut Line= 2
      2140557.54      402456.223     2139459.714      402316.728
#Sta/Elev= 30
       0 2684.44    50.3 2669.79   201.2 2628.72   261.6 2616.88   342.1 2599.57
   382.3 2589.97   442.7 2569.28   452.7 2564.33   462.8 2557.18     493  2533.7
     503  2527.1   513.1 2522.05   523.2  2519.2   533.2  2517.8   553.3 2516.38
   558.5  2516.5   573.5  2517.3   643.9 2522.94   794.8 2539.91   855.1 2547.23
   875.3    2551   885.3 2553.59   905.4 2560.48   915.5 2564.86   925.6 2570.39
   955.8 2588.78  1036.2 2632.91  1076.5 2656.02  1086.5 2660.82  1106.6  2668.9
#Mann= 3 , 0 , 0
       0      .1       0   558.5    .045       0   573.5      .1       0
Bank Sta=558.5,573.5
XS Rating Curve= 0 ,0
Exp/Cntr=0.3,0.1

Type RM Length L Ch R = 1 ,9765    ,430.5,431.7,433
XS GIS Cut Line= 2
     2140605.633      402193.339     2139502.958      402093.536
#Sta/Elev= 30
       0 2695.43    20.1 2691.73     151  2664.5   211.4 2651.32   241.6 2643.07
   281.8  2630.2     302  2623.1   332.2 2610.29   382.5 2586.15     463  2549.3
   483.1 2541.95   523.4  2530.6   533.5 2526.35   543.5 2519.78   553.6  2512.5
   563.7 2508.89   573.7 2509.28   579.8 2510.07   593.8 2511.69   603.9 2512.27
     624 2512.79   654.2 2512.81   674.4  2513.9   865.6 2536.88   875.7 2538.58
   885.8 2541.88     926 2561.69   966.3 2582.19  1066.9 2634.45  1107.2 2654.88
#Mann= 3 , 0 , 0
       0      .1       0   563.7    .045       0   579.8      .1       0
Bank Sta=563.7,579.8
XS Rating Curve= 0 ,0
Exp/Cntr=0.3,0.1

Type RM Length L Ch R = 1 ,9333.3  ,431.1,418.6,405.9
XS GIS Cut Line= 2
     2140670.531       401829.89     2139605.176      401674.851
#Sta/Elev= 30
       0 2680.33    10.1 2677.38    20.1 2673.42    50.3 2660.23    90.6 2644.31
   130.8  2631.2     161 2619.07   191.2 2605.79   211.3 2595.12   261.6 2564.44
   291.8 2546.84   311.9 2536.12   342.1 2521.35   352.2  2517.5   372.3 2511.22
   412.5 2501.39   422.6 2499.96   452.8 2498.86   462.8 2498.81   467.8 2499.05
   593.6 2504.79   784.8 2509.29   794.9 2509.75   804.9 2511.71     815 2516.13
   865.3  2545.6   915.6  2573.5   925.7  2578.3   945.8 2586.35  1076.6 2641.37
#Mann= 3 , 0 , 0
       0      .1       0   452.8    .045       0   467.8      .1       0
Bank Sta=452.8,467.8
XS Rating Curve= 0 ,0
Exp/Cntr=0.3,0.1

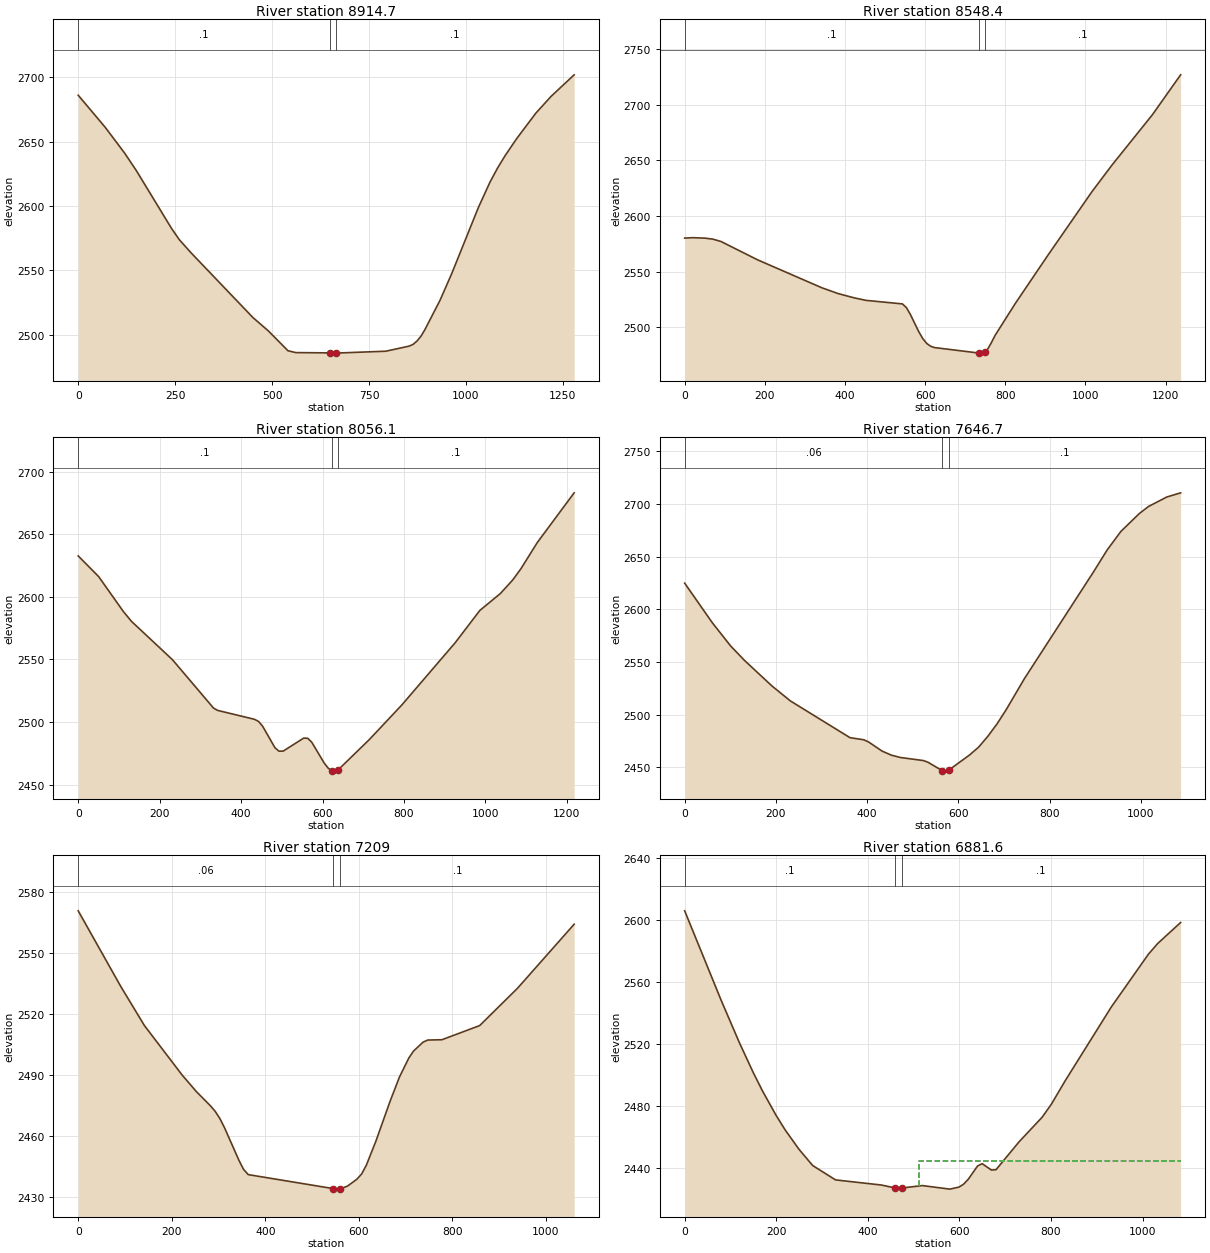
Type RM Length L Ch R = 1 ,8914.7  ,356.4,366.3,375.5
XS GIS Cut Line= 4
     2140780.732      401453.254      2140281.34      401347.237
     2139940.972      401500.682     2139548.509      401545.206
#Sta/Elev= 30
       0 2685.88    70.1 2660.85   120.1 2640.84   150.2  2627.3   240.2 2582.83
   260.3 2574.03   290.3 2563.91   450.5 2513.52   490.5  2503.1   540.8 2487.79
     561 2486.32   649.5  2486.1   661.9 2485.91   664.5 2485.94   793.1 2487.39
   853.6 2491.36   863.7 2492.73   873.8 2495.32   883.9 2499.04   893.8    2504
   933.2 2526.98   962.9 2547.36    1032 2598.86  1061.6 2618.32  1081.4 2629.43
  1101.1 2639.13  1130.7 2652.23  1180.1 2671.98  1219.6 2685.06  1278.9  2701.7
#Mann= 3 , 0 , 0
       0      .1       0   649.5    .045       0   664.5      .1       0
Bank Sta=649.5,664.5
XS Rating Curve= 0 ,0
Exp/Cntr=0.3,0.1

Type RM Length L Ch R = 1 ,8548.4  ,491.5,492.3,493
XS GIS Cut Line= 2
     2140762.598      401100.331     2139525.277      401115.675
#Sta/Elev= 30
       0 2580.17    20.1 2580.55    50.3 2580.15    70.4 2579.22    90.5 2577.14
   181.1 2560.79     342  2535.6   382.3 2530.42   422.5 2526.55   452.7 2524.24
   543.3 2521.08   553.3 2517.75   563.4 2511.42   583.5 2496.54   593.6  2490.2
   603.6 2485.69   613.7 2483.04   623.7 2481.85   733.8 2476.97   744.5 2476.88
   748.8 2478.04   754.5 2479.57   764.6 2485.87   774.6 2492.87   824.9 2521.45
   905.4  2564.3  1016.1 2621.81  1066.4 2645.85    1167 2690.93  1237.4 2726.77
#Mann= 3 , 0 , 0
       0      .1       0   733.8    .045       0   748.8      .1       0
Bank Sta=733.8,748.8
XS Rating Curve= 0 ,0
Exp/Cntr=0.3,0.1

Type RM Length L Ch R = 1 ,8056.1  ,403,409.4,415.4
XS GIS Cut Line= 2
     2140750.043      400666.501     2139532.252      400646.972
#Sta/Elev= 30
       0 2632.75    50.3 2616.18   110.7 2588.38   130.8 2580.44   231.5 2549.77
   332.2 2511.15   342.2 2509.26   432.8 2502.14   442.9 2500.45     453 2496.55
   483.2  2479.4   493.2 2476.63   503.3 2476.68   553.6 2487.07   563.7 2486.97
   573.7 2483.76   603.9 2467.29     614 2463.05   623.6 2460.87   634.1  2460.7
   638.6 2461.79   714.7 2485.85   795.2 2513.74     926 2563.41   986.4 2589.17
  1036.8 2602.68    1067 2613.46  1087.1  2622.4  1127.4  2643.4    1218 2683.18
#Mann= 3 , 0 , 0
       0      .1       0   623.6    .045       0   638.6      .1       0
Bank Sta=623.6,638.6
XS Rating Curve= 0 ,0
Exp/Cntr=0.3,0.1

Type RM Length L Ch R = 1 ,7646.7  ,439.8,437.7,435.2
XS GIS Cut Line= 2
     2140779.337      400447.494     2139738.704       400133.63
#Sta/Elev= 30
       0 2624.83    60.4 2587.38   100.6 2565.33   130.8 2551.68   191.2 2527.36
   231.5 2513.18   362.3 2478.28   392.5 2476.29   402.6 2474.33   432.8 2465.51
   452.9 2461.71     473 2459.46   523.3 2456.57   533.4 2454.93   564.3 2447.04
   573.7 2446.55   579.3 2447.68     624 2461.75   644.1 2469.24   664.2 2479.47
   684.4 2491.24   704.5 2504.73   744.8 2534.43   895.7 2635.28   925.9  2656.3
   956.1 2673.93   996.4 2690.85  1016.5 2697.55  1056.7 2706.54  1086.9  2710.5
#Mann= 3 , 0 , 0
       0     .06       0   564.3    .045       0   579.3      .1       0
Bank Sta=564.3,579.3
XS Rating Curve= 0 ,0
Exp/Cntr=0.3,0.1

Type RM Length L Ch R = 1 ,7209    ,310.5,327.4,344.3
XS GIS Cut Line= 2
     2140861.639      399960.656     2139819.611      399765.363
#Sta/Elev= 30
       0  2570.9    90.9 2533.73   141.4  2514.5   222.1 2490.14   252.4 2482.02
   282.7 2474.97   292.8 2472.27   302.9 2468.69     313 2464.08   343.3 2448.31
   353.4 2443.73   363.5 2441.12   545.4 2434.23   555.3 2433.98   560.4 2434.14
   575.5 2435.45   595.7 2438.84   605.8 2441.41   615.9 2445.72   636.1 2457.41
   666.4 2477.01   686.6 2489.06   706.8  2498.5   716.9 2501.92   737.1 2506.27
   747.2 2507.33   777.5 2507.48   858.2 2514.44     939 2532.77  1060.2 2564.31
#Mann= 3 , 0 , 0
       0     .06       0   545.4    .045       0   560.4      .1       0
Bank Sta=545.4,560.4
XS Rating Curve= 0 ,0
Exp/Cntr=0.3,0.1

Type RM Length L Ch R = 1 ,6881.6  ,304,288.6,274
XS GIS Cut Line= 4
     2140882.564      399747.229     2140517.087      399645.398
     2140394.331      399487.768     2139892.149      399444.525
#Sta/Elev= 30
       0  2606.1    79.9 2548.17   119.8 2520.76   149.8 2501.63   169.7 2489.93
   199.7    2474   219.6 2464.56   249.6 2452.14   279.6 2441.62   329.5 2432.34
   429.4 2429.04   458.7 2427.21   473.7 2427.08   519.2 2428.67   579.2 2426.38
   599.4 2427.72   609.4 2429.62   619.5  2432.8   639.7 2441.33   649.8 2442.83
   669.9 2438.71     680 2438.91   730.4 2456.95   780.8 2472.82     801 2481.27
   831.2 2496.41     932 2544.09  1012.7 2578.02  1032.8 2584.91  1083.2 2598.56
#Mann= 3 , 0 , 0
       0      .1       0   458.7    .045       0   473.7      .1       0
#XS Ineff= 2 , 0
                          511.43         2444.61
Permanent Ineff=
       F       F
Bank Sta=458.7,473.7
XS Rating Curve= 0 ,0
Exp/Cntr=0.3,0.1

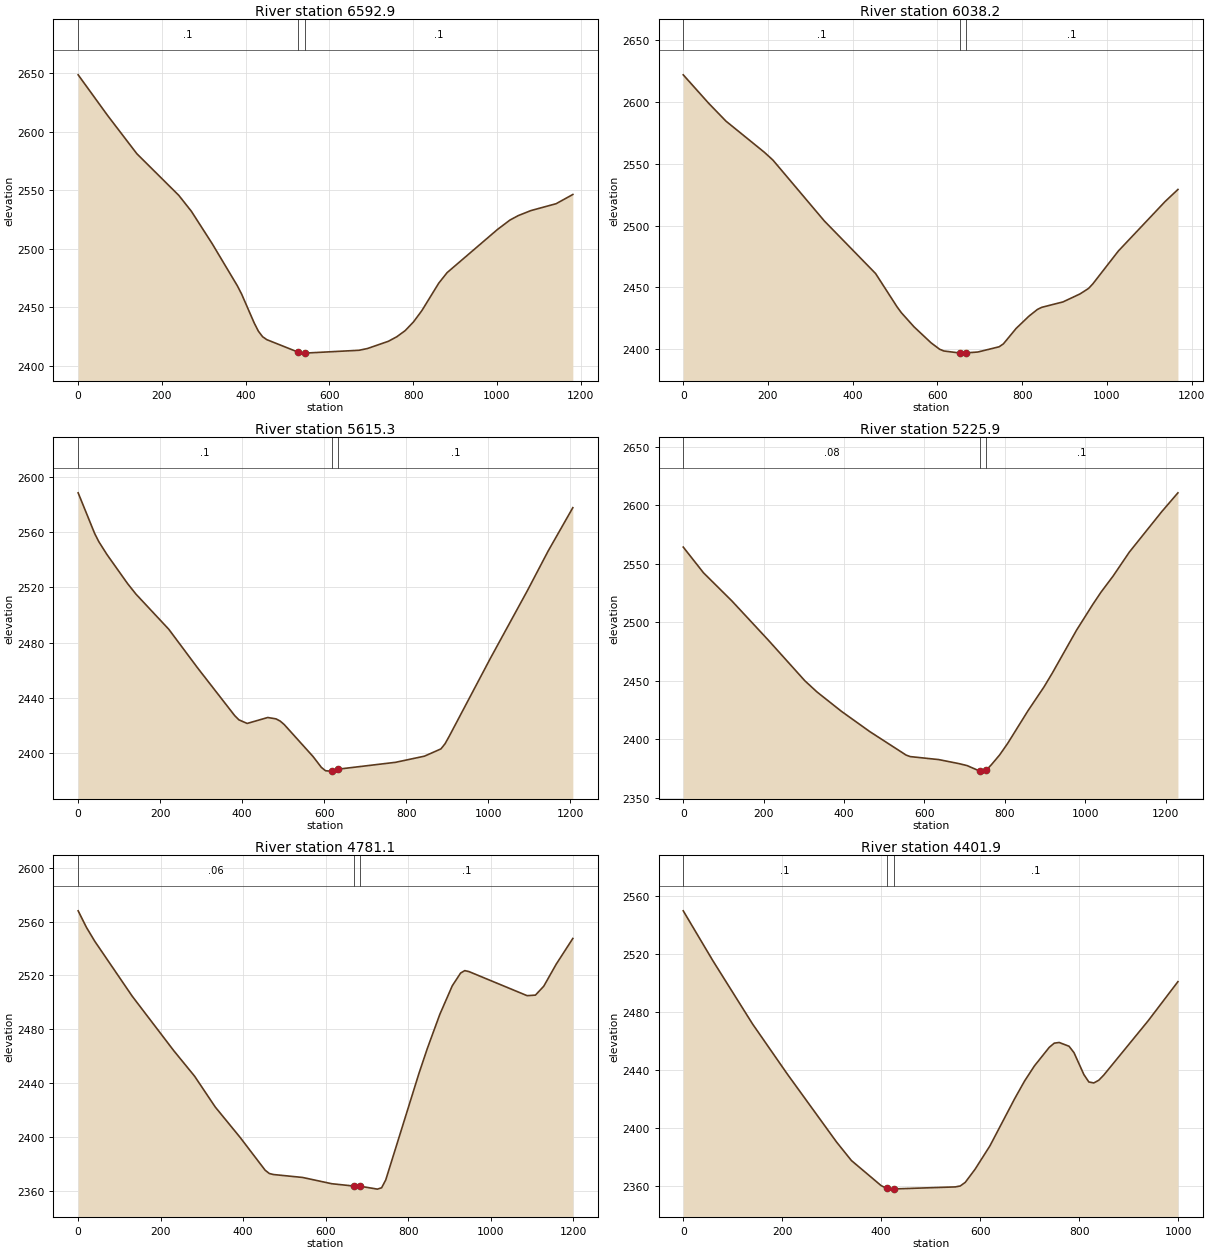
Type RM Length L Ch R = 1 ,6592.9  ,566.1,554.7,542.7
XS GIS Cut Line= 2
      2141073.42      399415.575     2139904.691      399242.679
#Sta/Elev= 30
       0 2648.63    70.1 2614.01   140.2 2581.21   240.3 2545.67   270.3 2532.11
   320.4  2504.2   380.5  2468.2   390.5 2461.23   420.5 2436.59   430.5 2429.57
   440.5 2424.87   450.6 2422.36   525.8 2411.64   540.7 2410.86   540.8 2410.86
   670.8  2413.3   690.8 2414.78   740.9 2420.98   760.9 2424.83     781 2430.08
     801 2437.59     821 2447.26   861.1 2470.59   881.1 2479.62  1001.2 2516.44
  1031.3 2524.57  1051.3  2528.4  1081.3 2532.65  1141.4 2538.51  1181.4  2546.4
#Mann= 3 , 0 , 0
       0      .1       0   525.8    .045       0   540.8      .1       0
Bank Sta=525.8,540.8
XS Rating Curve= 0 ,0
Exp/Cntr=0.3,0.1

Type RM Length L Ch R = 1 ,6038.2  ,426.5,422.9,419.7
XS GIS Cut Line= 3
     2141107.249      399030.702     2140648.646      398775.923
     2140029.023      398947.135
#Sta/Elev= 30
       0 2621.94    60.5 2598.76   100.9 2584.47   191.7 2559.23   211.9  2552.9
   332.9 2503.79     454 2461.21   504.4 2434.41   514.5 2429.66   544.7 2418.11
   584.9 2405.18     605 2400.02     615 2398.59   653.5 2396.91   655.2 2396.85
   668.5 2397.06   695.4 2397.76   745.6 2401.99   755.6 2404.34   785.8 2416.88
   815.9 2426.75     836 2432.21     846 2433.88   896.3 2438.28   936.4 2444.72
   956.5 2449.16   966.6 2452.83  1026.8 2479.39  1137.3 2519.48  1167.5 2529.21
#Mann= 3 , 0 , 0
       0      .1       0   653.5    .045       0   668.5      .1       0
Bank Sta=653.5,668.5
XS Rating Curve= 0 ,0
Exp/Cntr=0.3,0.1

Type RM Length L Ch R = 1 ,5615.3  ,381.9,389.4,395.9
XS GIS Cut Line= 2
     2140950.305      398162.415     2139851.696      398661.782
#Sta/Elev= 30
       0 2588.62    40.2 2559.19    50.3 2553.25    70.4 2543.81   120.7 2522.74
   140.8 2515.22   221.2 2489.62   291.6 2461.55   382.2  2426.9   392.2 2423.94
   412.3 2421.34   462.6 2425.65   482.7 2424.65   492.8 2423.07   502.8 2420.52
   573.2 2397.29   593.3 2389.48   603.4 2387.05   613.4 2386.75   619.6 2387.13
   634.6 2388.18   774.4 2393.15   844.7 2397.59     885 2402.86     895 2406.59
   905.1 2411.97  1005.6 2468.55  1096.2 2517.82  1146.4  2546.3  1206.8 2577.85
#Mann= 3 , 0 , 0
       0      .1       0   619.6    .045       0   634.6      .1       0
Bank Sta=619.6,634.6
XS Rating Curve= 0 ,0
Exp/Cntr=0.3,0.1

Type RM Length L Ch R = 1 ,5225.9  ,432.9,444.8,456.6
XS GIS Cut Line= 2
      2140874.89      398062.541     2139651.949      398197.065
#Sta/Elev= 30
       0 2564.17    50.4 2542.19     121 2518.15   211.8 2484.58   302.5 2449.93
   332.8 2440.35   393.3 2423.88   463.9 2406.53   554.6 2386.39   564.7 2385.16
   635.3 2382.61   685.8 2379.16   705.9 2377.48   737.1 2372.85   746.3 2372.75
   752.1 2373.79   756.3 2374.55   766.4 2378.25   786.6 2386.46   806.8 2396.42
   857.2 2424.23   897.5 2444.84   917.7 2456.42   978.2  2493.2  1018.5 2515.13
  1038.7  2525.5    1069 2539.36  1109.3 2559.81    1190  2594.4  1230.3 2610.52
#Mann= 3 , 0 , 0
       0     .08       0   737.1    .045       0   752.1      .1       0
Bank Sta=737.1,752.1
XS Rating Curve= 0 ,0
Exp/Cntr=0.3,0.1

Type RM Length L Ch R = 1 ,4781.1  ,382.5,379.2,375.9
XS GIS Cut Line= 2
     2140903.979      398002.674     2139806.706      397519.144
#Sta/Elev= 30
       0 2567.94    20.2  2555.6    40.3 2545.35     131 2504.59   231.8 2464.11
   282.1 2445.25   332.5 2422.24     393  2399.6   453.4 2375.34   463.5 2372.93
   473.6 2372.18   544.1 2370.01   614.7 2365.36   668.4 2363.63   683.4  2363.5
   725.5 2361.35   735.6 2362.37   745.6 2368.17   826.3 2447.44   846.4 2465.75
   876.6 2491.04   906.9 2512.31     927 2521.72   937.1 2523.55   947.2 2522.85
  1088.2 2504.97  1108.4 2505.36  1128.6 2511.97  1158.8 2528.34  1199.1 2547.43
#Mann= 3 , 0 , 0
       0     .06       0   668.4    .045       0   683.4      .1       0
Bank Sta=668.4,683.4
XS Rating Curve= 0 ,0
Exp/Cntr=0.3,0.1

Type RM Length L Ch R = 1 ,4401.9  ,242.9,237.8,232.2
XS GIS Cut Line= 2
     2140999.222      397673.238     2140047.367      397367.503
#Sta/Elev= 30
       0 2549.57      60 2515.19     140 2471.76     210 2437.43   309.9 2390.46
   339.9 2377.74   399.9 2360.51   411.2 2358.56   419.9 2358.07   426.2 2358.21
   549.9 2359.59   559.9 2360.25   569.9 2362.71   589.8 2371.75   619.8 2387.82
   669.8 2420.28   689.8 2432.43   709.8 2442.88   739.8 2455.65   749.8  2458.5
   759.8 2458.98   779.8 2456.37   789.8 2451.94   809.8 2436.84   819.8  2431.8
   829.8 2431.14   839.8 2432.99   849.8  2436.5   939.8 2473.98   999.8 2500.83
#Mann= 3 , 0 , 0
       0      .1       0   411.2    .045       0   426.2      .1       0
Bank Sta=411.2,426.2
XS Rating Curve= 0 ,0
Exp/Cntr=0.3,0.1

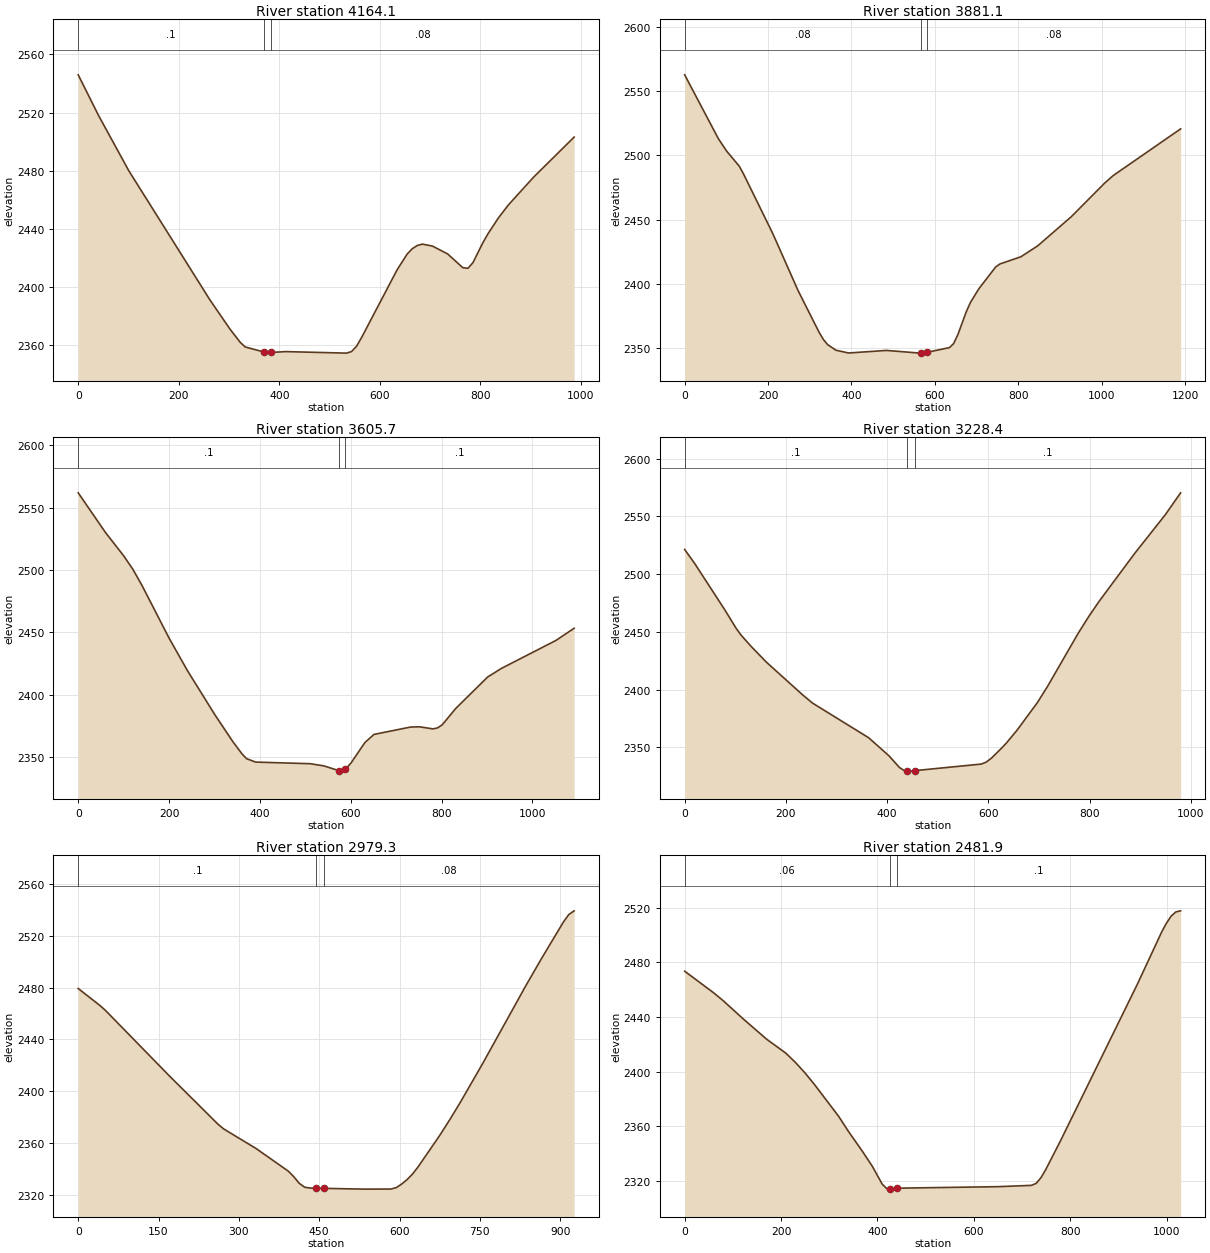
Type RM Length L Ch R = 1 ,4164.1  ,289.1,283.1,277.1
XS GIS Cut Line= 2
     2141076.096      397354.836     2140090.741      397305.515
#Sta/Elev= 30
       0 2545.98    40.3 2518.09   100.7  2479.9   261.8 2391.12     302 2370.87
   322.2 2361.83   332.2 2358.59   368.8  2355.2   383.8 2354.82   412.8  2355.4
   533.6 2354.35   543.6 2355.38   553.7 2359.08   563.8 2365.12   634.2 2411.59
   654.4 2422.55   664.4 2426.21   674.5 2428.45   684.6 2429.42   704.7 2428.06
   734.9 2422.66   765.1 2413.19   775.2 2412.75   785.2 2416.61   805.4 2430.63
   815.4 2436.64   835.6 2447.28   855.7 2456.36     906 2475.55   986.6 2503.12
#Mann= 3 , 0 , 0
       0      .1       0   368.8    .045       0   383.8     .08       0
Bank Sta=368.8,383.8
XS Rating Curve= 0 ,0
Exp/Cntr=0.3,0.1

Type RM Length L Ch R = 1 ,3881.1  ,276.8,275.4,273.9
XS GIS Cut Line= 2
     2141190.816      396963.933     2140026.985      397208.521
#Sta/Elev= 30
       0 2562.58    80.6 2513.04   100.8 2503.22     131 2491.53   141.1 2485.54
   211.6 2438.94   272.1 2394.74   322.5 2362.34   332.6 2356.85   342.7 2352.88
   362.8 2348.48   393.1 2346.32   483.8 2348.32   564.4 2346.22   566.3 2346.24
   581.3 2346.86   634.9 2350.51     645 2353.63   655.1 2360.58   675.3 2378.39
   685.3 2385.64   705.5 2396.26   745.8  2413.2   755.9 2415.53   806.3 2421.14
   846.6 2429.63   927.2  2452.3  1007.8 2478.61    1028 2484.34  1189.3 2520.56
#Mann= 3 , 0 , 0
       0     .08       0   566.3    .045       0   581.3     .08       0
Bank Sta=566.3,581.3
XS Rating Curve= 0 ,0
Exp/Cntr=0.3,0.1

Type RM Length L Ch R = 1 ,3605.7  ,377.3,377.3,377.2
XS GIS Cut Line= 2
     2141104.828      396675.006     2140050.128      396957.973
#Sta/Elev= 30
       0  2561.9    60.1 2530.06   100.2 2511.34   120.2 2500.66   140.3 2487.74
   200.4 2445.16   240.4 2419.37   300.6 2384.11   340.6  2362.3   360.7  2352.5
   370.7  2348.7   390.7 2345.95   510.9 2344.65     541 2342.91   573.5 2339.11
   581.1  2338.7   588.5 2340.08   601.1 2345.45   631.2 2361.61   651.2 2368.13
   731.3 2374.02   751.4 2374.26   781.4 2372.56   791.4 2373.39   801.5 2375.86
   831.5 2389.05   901.6 2414.19   931.7 2421.05  1051.9 2443.51    1092 2453.29
#Mann= 3 , 0 , 0
       0      .1       0   573.5    .045       0   588.5      .1       0
Bank Sta=573.5,588.5
XS Rating Curve= 0 ,0
Exp/Cntr=0.3,0.1

Type RM Length L Ch R = 1 ,3228.4  ,245.6,249,252.3
XS GIS Cut Line= 2
     2140881.005      396344.309     2139935.264      396599.089
#Sta/Elev= 30
       0  2521.4    20.2 2508.97    80.8 2468.04     101 2453.49   111.1 2447.34
   131.3 2437.37   161.6 2423.68   232.2  2395.7   252.4 2388.31   363.5  2358.2
   403.9 2342.42   424.1 2332.49   434.2 2329.62     440 2329.44   444.3 2329.31
     455 2329.75   585.7 2335.42   595.8 2337.18   605.8 2340.53     626 2349.26
   636.1 2354.02   656.3  2364.7   696.7 2388.77   716.9 2402.91   777.5 2448.99
   797.7 2463.06   817.9 2476.07   888.6 2517.87   949.2  2551.5   979.5  2570.5
#Mann= 3 , 0 , 0
       0      .1       0     440    .045       0     455      .1       0
Bank Sta=440,455
XS Rating Curve= 0 ,0
Exp/Cntr=0.3,0.1

Type RM Length L Ch R = 1 ,2979.3  ,495.1,497.5,499.7
XS GIS Cut Line= 2
      2140871.49      396162.547     2139951.763      396268.945
#Sta/Elev= 30
       0 2479.37    40.2 2466.35    50.3 2462.67   171.1 2411.38   261.7 2374.11
   271.7 2370.72   332.1 2355.59   392.5    2338   402.6 2333.74   412.6 2328.69
   422.7 2325.68   432.7 2325.02   444.6 2324.92   459.6 2324.77   533.4 2324.18
   583.7 2324.23   593.8 2325.34   603.8 2328.07   613.9 2331.51     624 2335.77
     634 2341.08   674.3 2365.32   694.4 2378.34   714.5 2392.11   754.8 2421.11
   835.3 2481.26   865.5 2502.92   905.7  2530.7   915.8 2536.55   925.9 2539.46
#Mann= 3 , 0 , 0
       0      .1       0   444.6    .045       0   459.6     .08       0
Bank Sta=444.6,459.6
XS Rating Curve= 0 ,0
Exp/Cntr=0.3,0.1

Type RM Length L Ch R = 1 ,2481.9  ,305.6,301.5,297.3
XS GIS Cut Line= 3
     2140980.878       395997.81     2140719.984      395796.024
      2140020.87      395816.407
#Sta/Elev= 30
       0  2473.6      60 2457.82      80 2451.99   119.9 2439.18   169.9 2423.86
   209.9 2413.62   229.9 2406.79   249.9 2399.06   269.8 2390.47   319.8 2367.22
   339.8 2356.34   369.8 2341.26   389.8 2330.57   409.8 2317.78   419.8 2314.26
   425.9 2314.14   429.7 2314.06   440.9 2314.75   649.6 2315.85   719.5 2316.81
   729.5 2318.28   739.5 2322.48   749.5 2328.51   779.4 2349.05   939.3 2463.97
   989.3 2501.86   999.3 2508.47  1009.2 2513.79  1019.2 2516.98  1029.2  2517.8
#Mann= 3 , 0 , 0
       0     .06       0   425.9    .045       0   440.9      .1       0
Bank Sta=425.9,440.9
XS Rating Curve= 0 ,0
Exp/Cntr=0.3,0.1