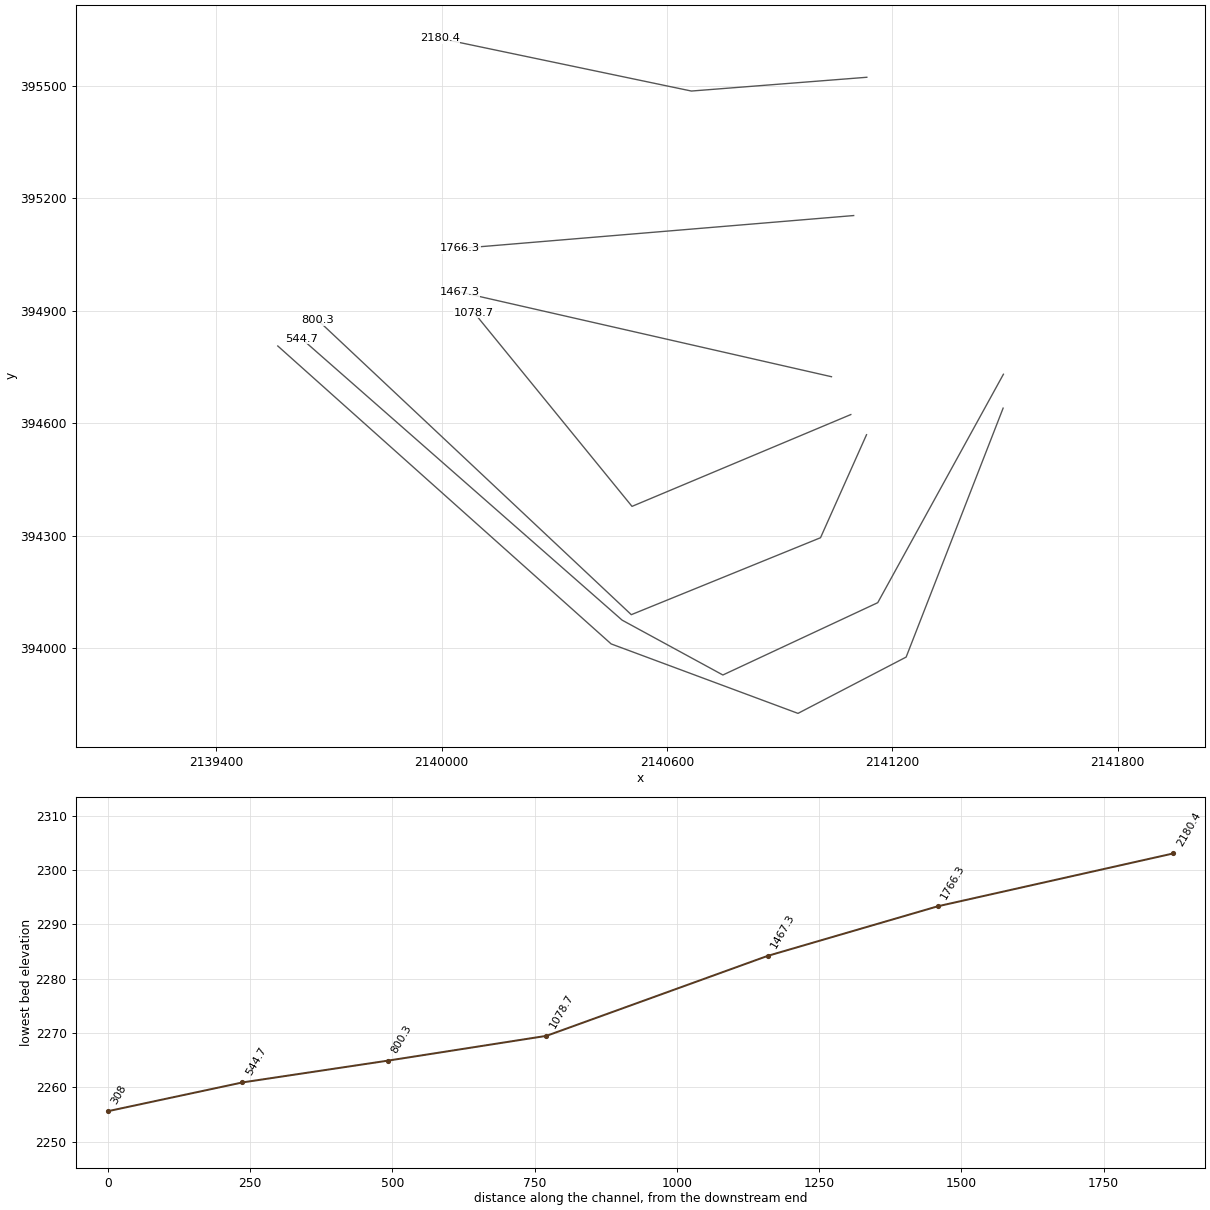
HEC-RAS study PantCampCk.prj: PantCampCk

--- PantCampCk.g01 (geometry) --- (continued)

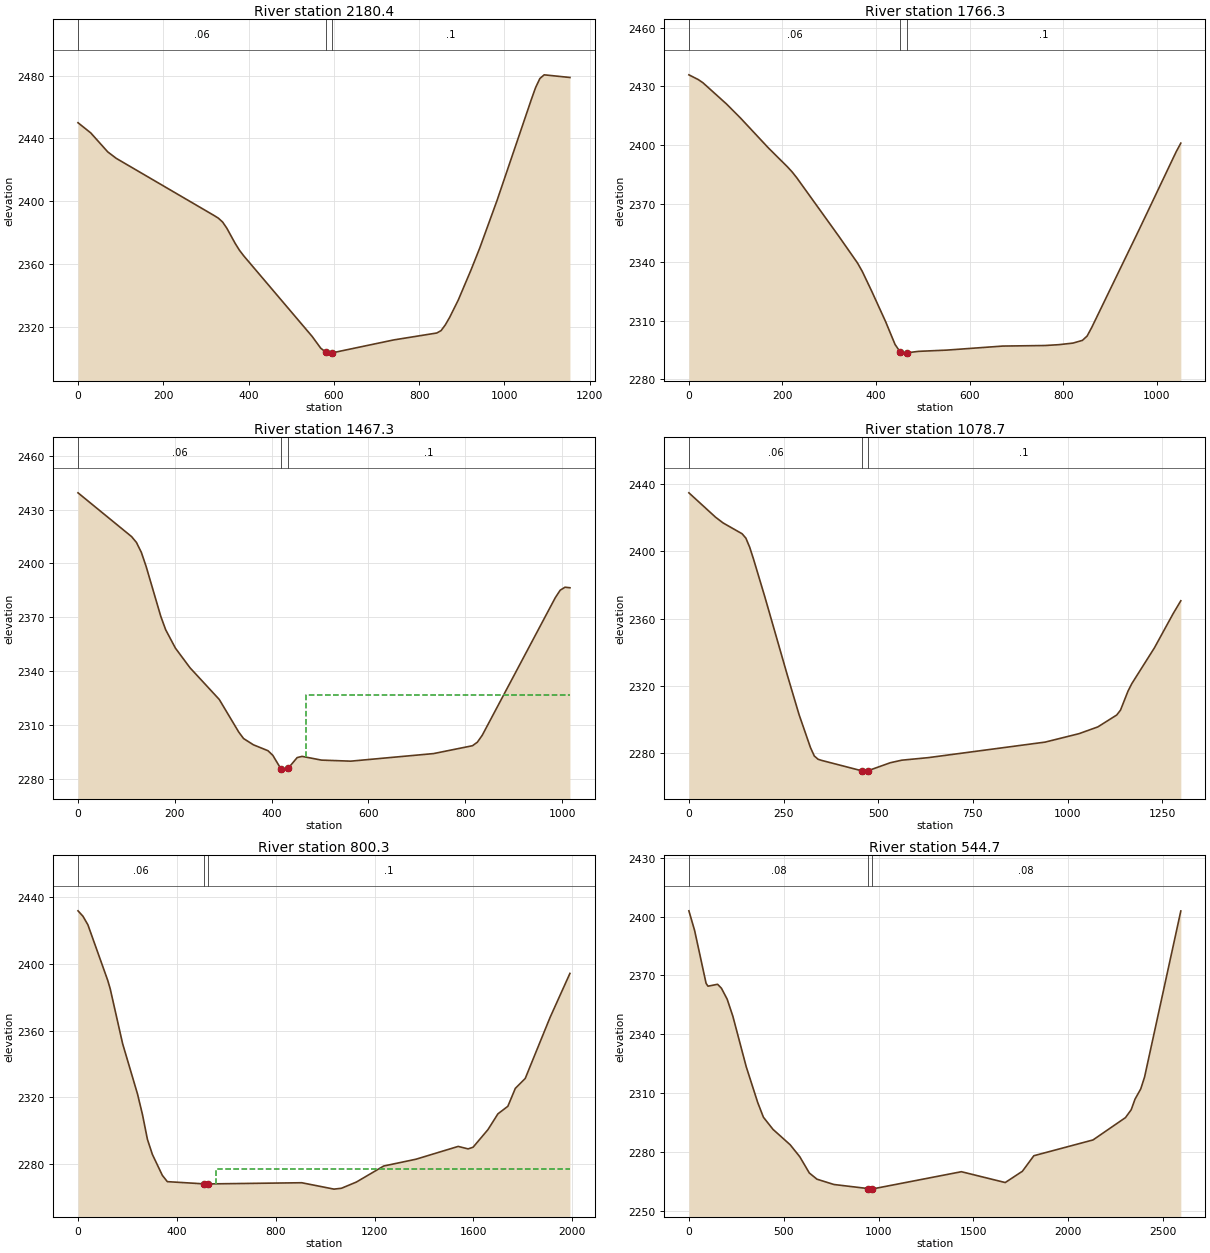
Type RM Length L Ch R = 1 ,2180.4  ,407.3,414.1,420.7
XS GIS Cut Line= 3
     2141132.085      395522.954     2140664.952      395486.213
     2139994.373      395626.851
#Sta/Elev= 30
       0 2449.96    29.9 2443.47    69.8 2431.36    89.7 2427.25     319 2390.83
     329 2389.15     339  2386.7   348.9 2382.76   368.9 2372.89   378.8 2368.59
   388.8 2365.05   549.2 2313.68   569.3 2306.19   581.7 2303.59   589.5 2303.06
   596.7 2303.27   740.6 2311.49   841.4 2315.89   851.5 2317.42   861.5  2321.1
   871.6 2325.86   891.8 2336.91     922 2356.28   942.2 2370.09   982.4 2400.14
  1063.1 2464.72  1073.1 2472.35  1083.2 2478.15  1093.3 2480.51  1153.7 2478.81
#Mann= 3 , 0 , 0
       0     .06       0   581.7    .045       0   596.7      .1       0
Bank Sta=581.7,596.7
XS Rating Curve= 0 ,0
Exp/Cntr=0.3,0.1

Type RM Length L Ch R = 1 ,1766.3  ,306,299,292.1
XS GIS Cut Line= 2
     2141097.058      395153.981     2140049.405      395066.336
#Sta/Elev= 30
       0 2435.98      20 2433.55      30 2431.92    80.1 2421.09   110.1 2413.88
   170.2 2398.44   210.3  2388.9   220.3 2386.31   230.3  2383.3   320.4 2353.24
   360.4 2339.51   370.5 2335.25   390.5 2325.18   420.5 2309.43   440.6 2297.77
   450.9 2294.15   460.6 2293.33   465.9 2293.48   490.6 2294.24   550.7 2294.87
   670.8 2296.95     761 2297.23     791 2297.67     821 2298.48     841 2299.87
   851.1  2302.1   861.1 2306.58   961.2 2356.14  1041.3 2396.51  1051.3 2400.96
#Mann= 3 , 0 , 0
       0     .06       0   450.9    .045       0   465.9      .1       0
Bank Sta=450.9,465.9
XS Rating Curve= 0 ,0
Exp/Cntr=0.3,0.1

Type RM Length L Ch R = 1 ,1467.3  ,374.3,388.6,402.4
XS GIS Cut Line= 2
     2141037.949      394723.913     2140047.367      394950.157
#Sta/Elev= 30
       0 2439.36   110.7 2414.94   120.7  2411.7   130.8 2406.19   140.8 2398.23
     171 2370.48   181.1 2363.01   201.2 2352.77   231.4  2341.8   291.8 2324.15
     332 2305.98     342 2302.36   362.2 2298.89   392.4 2295.58   402.4    2293
   419.3 2285.38   422.5  2284.2   434.3 2285.86   452.7 2291.75   462.8 2292.42
     503 2290.34   563.4 2289.76   734.4 2293.98   814.9 2298.37   824.9 2300.34
     835 2304.21   985.9 2380.92     996 2385.07    1006 2386.74  1016.1 2386.44
#Mann= 3 , 0 , 0
       0     .06       0   419.3    .045       0   434.3      .1       0
#XS Ineff= 2 , 0
                          471.47         2326.44
Permanent Ineff=
       F       F
Bank Sta=419.3,434.3
XS Rating Curve= 0 ,0
Exp/Cntr=0.3,0.1

Type RM Length L Ch R = 1 ,1078.7  ,278.6,278.5,278.2
XS GIS Cut Line= 3
     2141089.439      394622.936     2140506.805      394377.931
     2140086.093      394895.125
#Sta/Elev= 30
       0 2434.75    70.2 2420.32    90.3 2416.87   140.5 2410.44   150.5 2407.82
   160.5 2402.45   170.6 2395.41   200.6 2372.91   260.8 2325.79   290.9 2303.03
     321 2283.48   331.1 2278.49   341.1 2276.53   351.1 2275.82   456.6 2269.68
   461.5 2269.49   471.6 2269.63   531.7 2274.47   561.8 2275.98     632  2277.5
   940.5 2286.72  1030.1 2291.74  1079.8 2295.76  1129.6 2302.82  1139.5  2305.7
  1159.4 2317.02  1169.4 2321.45  1229.1  2342.7  1278.8 2363.12  1298.8 2370.65
#Mann= 3 , 0 , 0
       0     .06       0   456.6    .045       0   471.6      .1       0
Bank Sta=456.6,471.6
XS Rating Curve= 0 ,0
Exp/Cntr=0.3,0.1

Type RM Length L Ch R = 1 ,800.3   ,256.6,255.6,254.4
XS GIS Cut Line= 4
     2141131.269      394569.155     2141008.766      394294.271
      2140504.93      394088.954     2139670.911        394874.2
#Sta/Elev= 30
       0  2431.9    20.1 2428.64    40.1 2423.49   120.4 2390.12   130.4 2385.05
   180.6 2352.15   240.8 2321.98   260.8  2309.7   280.9 2294.79     301 2285.72
   341.2 2273.21   361.4 2269.42   510.8 2268.08   525.8 2268.05   905.3 2268.76
  1035.9 2264.93  1066.1 2265.45  1126.4 2269.18  1236.9 2278.79  1367.5 2282.87
  1538.4 2290.56  1578.5 2289.07  1598.6 2290.07  1658.9 2300.65  1699.1  2310.1
  1739.3 2314.63  1769.5 2325.37  1809.6 2331.33  1910.1 2367.94  1990.5 2394.36
#Mann= 3 , 0 , 0
       0     .06       0   510.8    .045       0   525.8      .1       0
#XS Ineff= 2 , 0
                          559.89         2277.12
Permanent Ineff=
       F       F
Bank Sta=510.8,525.8
XS Rating Curve= 0 ,0
Exp/Cntr=0.3,0.1

Type RM Length L Ch R = 1 ,544.7   ,238.9,236.7,232
XS GIS Cut Line= 5
     2141495.789      394730.499     2141161.148      394120.974
     2140748.795      393928.003     2140480.543      394074.322
     2139627.015      394825.427
#Sta/Elev= 30
       0 2402.99    30.2 2392.94    90.7 2365.94   100.8 2364.52   151.2 2365.49
   171.3  2363.5   201.6 2357.92   231.8 2349.16   302.3 2323.38   362.8 2305.13
     393  2297.6   443.4 2291.42   534.1 2283.55   584.5 2277.46   634.9 2269.15
   675.2 2265.99   764.6 2263.28   946.1 2261.19   962.6 2260.92  1436.5 2269.81
  1667.5 2264.28    1758 2270.04  1818.4 2277.97  2130.3 2286.03  2301.4 2297.43
  2331.5 2301.45  2351.7 2306.86  2381.8 2312.06    2402 2318.14  2593.1 2402.91
#Mann= 3 , 0 , 0
       0     .08       0   946.1    .045       0   962.6     .08       0
Bank Sta=946.1,962.6
XS Rating Curve= 0 ,0
Exp/Cntr=0.3,0.1

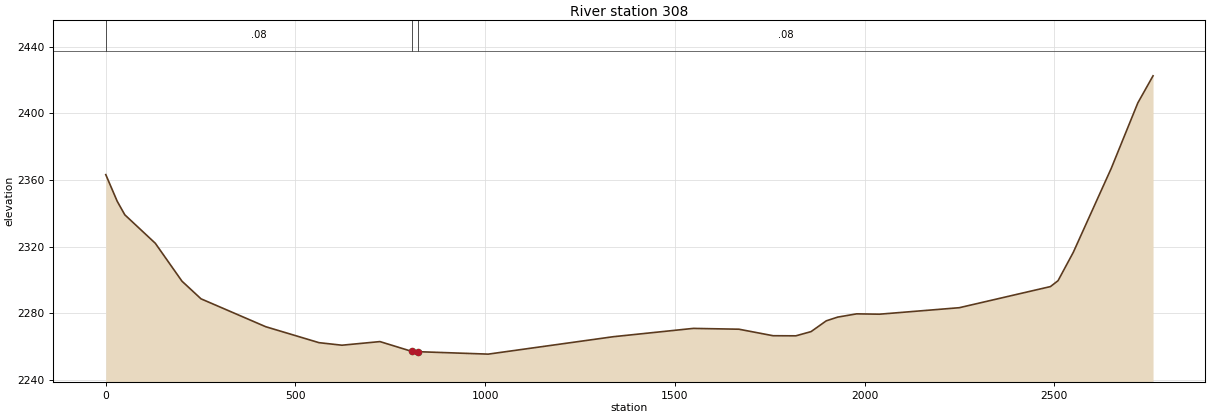
Type RM Length L Ch R = 1 ,308     ,307.8,308,310.9
XS GIS Cut Line= 5
     2141495.023      394640.089     2141236.777      393975.821
     2140948.765      393825.579     2140451.279      394010.917
      2139563.61      394805.918
#Sta/Elev= 30
       0 2363.32    30.1 2347.34    50.2  2339.2   130.5 2322.14   200.8 2299.39
     251  2288.8   421.6 2272.06   562.1 2262.49   622.4 2260.97   722.6 2263.14
   807.3 2257.21   822.3 2257.09    1008 2255.62    1338 2266.08  1548.4 2271.06
  1668.6 2270.57  1758.7 2266.66  1818.8  2266.6  1858.8 2269.13  1898.9  2275.6
  1928.9 2277.83    1979 2279.78  2039.1 2279.58  2249.4 2283.47  2489.7 2296.15
  2509.7 2299.68  2549.8 2316.66  2649.9 2367.07    2720 2406.36  2760.1  2422.6
#Mann= 3 , 0 , 0
       0     .08       0   807.3    .045       0   822.3     .08       0
Bank Sta=807.3,822.3
XS Rating Curve= 0 ,0
Exp/Cntr=0.3,0.1

Chan Stop Cuts=-1
Use User Specified Reach Order=0
Composite Channel Slope=5